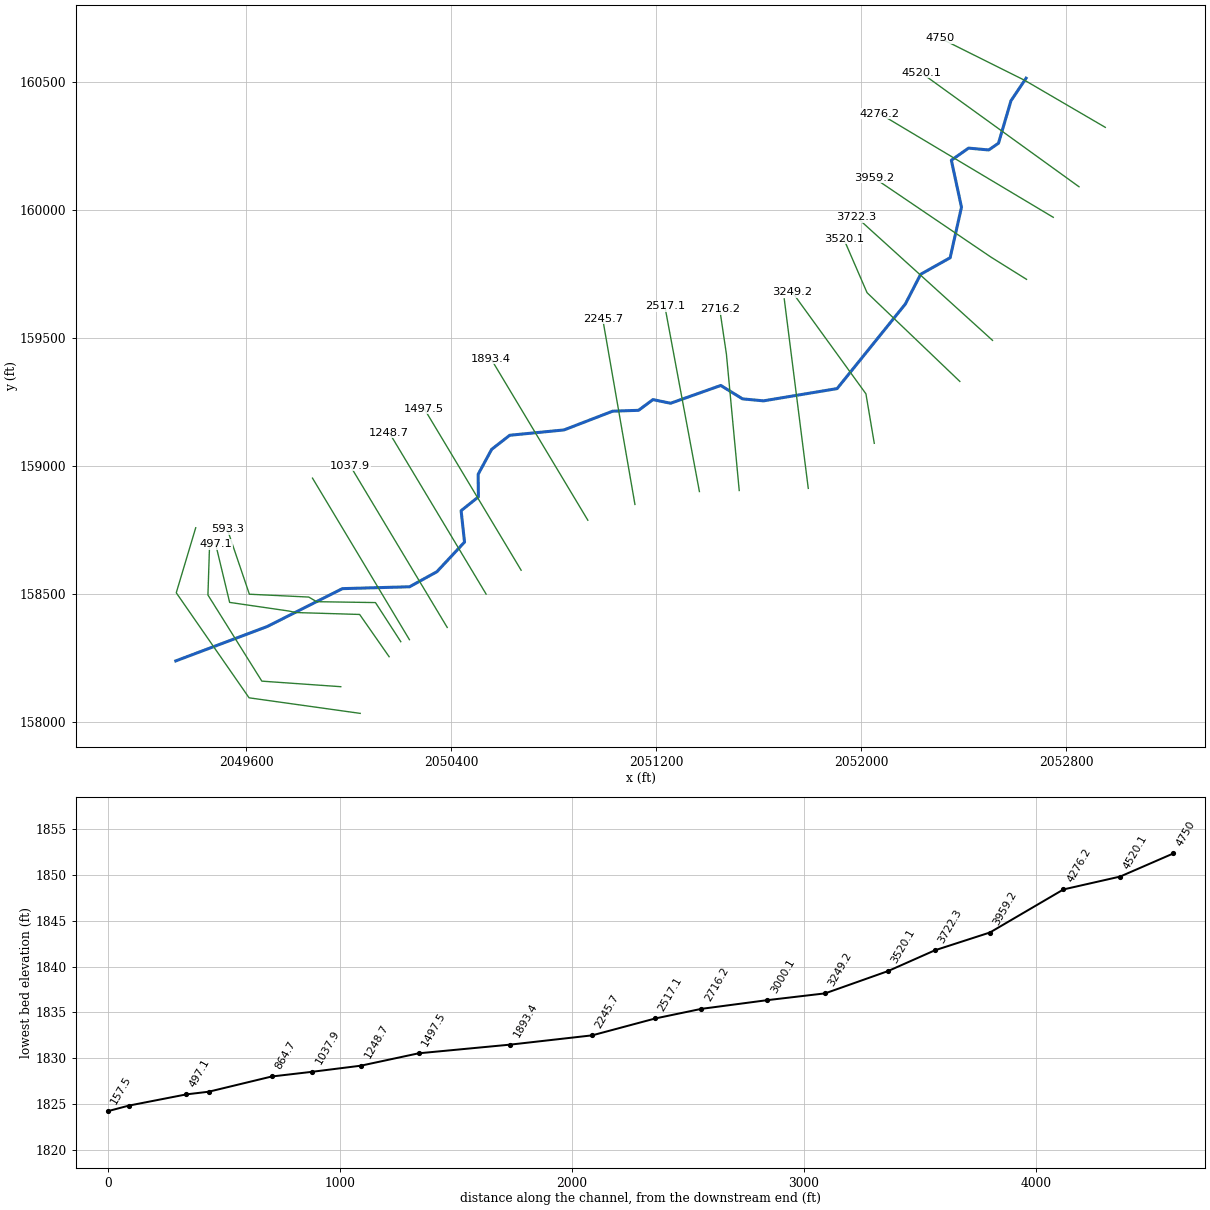
--- MUDRN.prj (project) ---

Proj Title=MUDRN
Current Plan=p01
Default Exp/Contr=0,0
English Units
Geom File=g01
Flow File=f01
Plan File=p01
BEGIN DESCRIPTION:
END DESCRIPTION:
DSS Export Rating Curves= 0
DSS Export Rating Curve Sorted= 0
DSS Export Volume Flow Curves= 0
DXF OffsetX= 0
DXF OffsetY= 0
DXF ScaleX= 0
DXF ScaleY= 0

--- MUDRN.p01 (plan) ---

Plan Title=Floodplain
Program Version=4.00
Geom File=g01
Flow File=f01
K Sum by GR=0
Std Step Tol=0.01
Critical Tol=0.01
Num of Std Step Trials=20
Max Error Tol=0.3
Flow Tol Ratio=0.001
Split Flow NTrial=30
Split Flow Tol=0.02
Split Flow Ratio=0.02
Log Output Level=0
Friction Slope Method=1
Unsteady Friction Slope Method=2
Unsteady Bridges Friction Slope Method=1
Global Log Level=0
CheckData=False
Run HTab=0
Run UNet=0
Run PostProcess=0
UNET Theta=0
UNET Theta Warmup=0
UNET ZTol=0
UNET ZSATol=0
UNET MxIter=0
UNET MaxInSteps=0
UNET DtIC=0
UNET DtMin=0
UNET MaxCRTS=0
UNET WFStab=0
UNET SFStab=0
UNET WFX=0
UNET SFX=0
UNET DSS MLevel=0
UNET DZMax Abort=0
UNET Convert EG Bridges=0
UNET Use Existing IB Tables=0
UNET Froude Limit=0
UNET Froude Power=0
Write IC File=0
Echo Input=False
Echo Output=False
Write Detailed=0

--- MUDRN.f01 (steady flow) ---

Flow Title=NFF Regression Equation
Program Version=4.00
Number of Profiles=1
Profile Names=P100yr
River Rch & RM=MUDRN,Main      ,4750
538.4639
River Rch & RM=MUDRN,Main      ,593.3
586.7046
River Rch & RM=MUDRN,Main      ,248.2
588.0701
Boundary for River Rch & Prof#=MUDRN,Main      ,1
Up Type=0
Dn Type=3
Dn Slope=0.005843

--- MUDRN.g01 (geometry) ---

Geom Title=USGS 10m DEM
Program Version=4.10

River Reach=MUDRN           ,Main
Reach XY= 30
     2052644.468      160513.587     2052585.318      160425.497
      2052536.59      160259.629     2052498.339       160233.31
     2052419.693      160240.601     2052352.506      160193.205
     2052392.089      160009.872     2052347.818      159812.476
     2052232.714      159747.893     2052172.992      159631.921
     2051906.412      159301.539     2051618.652      159253.622
     2051536.881      159261.434     2051452.245      159313.726
     2051256.152      159244.247     2051187.141      159258.518
     2051131.152      159216.643     2051030.228      159213.383
     2050840.006       159140.08     2050628.027      159119.247
     2050557.454      159064.247      2050504.68      158966.877
     2050505.631      158878.622     2050438.183      158824.664
     2050451.464       158702.06     2050343.652      158586.435
     2050236.881       158527.58     2049974.413      158520.332
     2049681.412       158372.58     2049323.991       158238.15

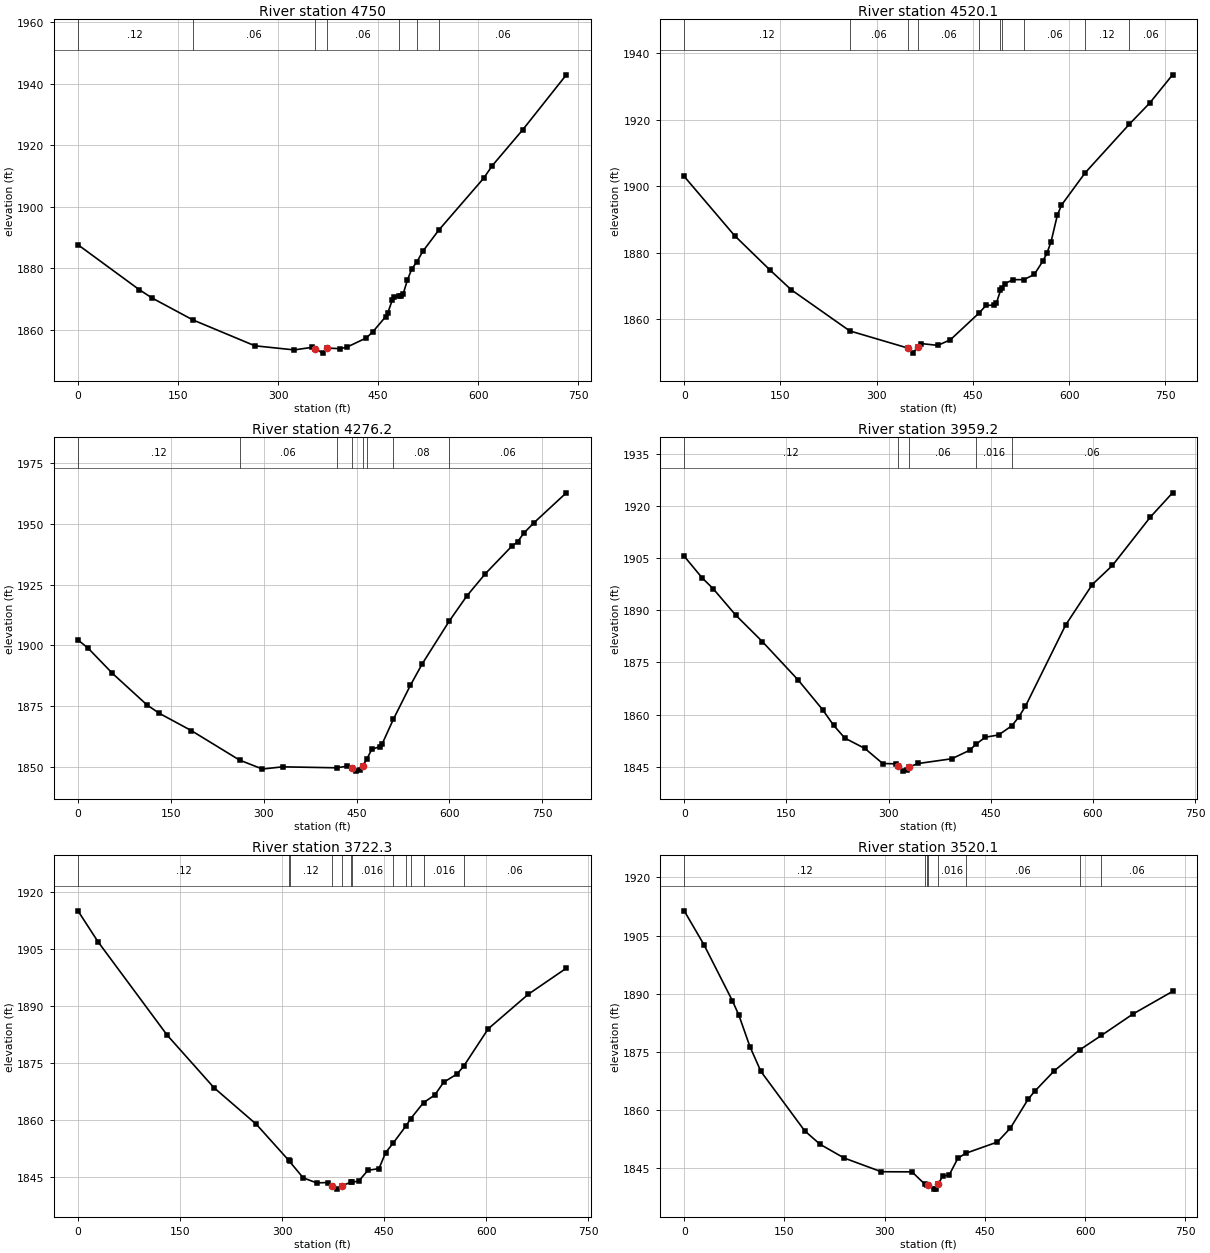
Type RM Length L Ch R = 1 ,4750    ,230.4,230,224.5
XS GIS Cut Line= 3
     2052953.647      160321.673     2052639.763      160504.848
     2052310.029      160669.249
#Sta/Elev= 30
       0  1887.6    91.7 1873.01   111.3 1870.25  172.031863.171   265.2 1854.73
   324.1  1853.4   350.3 1854.21   355.9 1853.74   366.7 1852.35   373.2    1854
   392.8  1853.8   402.6 1854.25   431.9 1857.26   441.7 1859.22   461.2 1864.22
   464.5 1865.52     471 1869.55   474.3 1870.74  480.511870.874   484.1 1870.84
   487.3 1871.54   493.8 1876.14   500.4 1879.77  508.041882.047   516.7 1885.41
  541.051892.427     608 1909.21     621 1913.33   666.7 1925.01   731.9 1942.85
#Mann= 7 ,-1 , 0
       0     .12       0  172.03     .06       0   355.9    .045       0
   373.2     .06       0  480.51    .016       0  508.04     .12       0
  541.05     .06       0
Bank Sta=355.9,373.2
XS Rating Curve= 0 ,0
Exp/Cntr=0.3,0.1

Type RM Length L Ch R = 1 ,4520.1  ,240.9,243.8,244.9
XS GIS Cut Line= 2
     2052850.993      160089.695     2052233.796      160535.408
#Sta/Elev= 30
       0 1902.98    78.4  1885.2     134 1874.77   166.6 1868.92  258.051856.507
   349.1 1851.32   356.2 1849.82   364.1 1851.64   369.2  1852.7   395.4 1852.15
     415 1853.85  459.671861.879   470.5 1864.17   483.6 1864.27   486.8 1864.94
  493.051868.683  494.661869.386   499.9 1870.76     513 1871.92  529.491871.927
   545.7 1873.48   558.7 1877.39   565.3  1879.8   571.8 1883.26   581.6 1891.24
   588.1 1894.34  625.061904.074  694.081918.732   725.4    1925   761.3 1933.55
#Mann= 10 ,-1 , 0
       0     .12       0  258.05     .06       0   349.1    .045       0
   364.1     .06       0  459.67    .016       0  493.05     .06       0
  494.66     .08       0  529.49     .06       0  625.06     .12       0
  694.08     .06       0
Bank Sta=349.1,364.1
XS Rating Curve= 0 ,0
Exp/Cntr=0.3,0.1

Type RM Length L Ch R = 1 ,4276.2  ,317.7,317.1,314.3
XS GIS Cut Line= 2
     2052750.464      159970.357     2052073.205      160374.818
#Sta/Elev= 30
       0 1902.27    16.4 1898.89    55.6 1888.57   111.3 1875.64   130.9 1872.22
   183.3 1865.03  260.941852.958   297.9 1849.28   330.6 1850.18  417.811849.784
   435.3 1850.46   441.9  1849.8   448.4 1848.42     455 1848.93   459.8 1850.47
  466.241853.214   474.6 1857.33   487.7 1858.52     491 1859.39   509.51869.726
   536.8 1883.57   556.4 1892.59  599.891910.068   628.4 1920.42   657.9 1929.42
   700.5 1940.68   710.3  1942.6   720.1  1946.1   736.5 1950.36   788.8 1962.66
#Mann= 8 ,-1 , 0
       0     .12       0  260.94     .06       0  417.81     .12       0
   441.9    .045       0   459.8     .12       0  466.24    .016       0
   509.5     .08       0  599.89     .06       0
Bank Sta=441.9,459.8
XS Rating Curve= 0 ,0
Exp/Cntr=0.3,0.1

Type RM Length L Ch R = 1 ,3959.2  ,239.4,236.9,232.5
XS GIS Cut Line= 3
     2052646.122      159728.117     2052507.233      159814.922
     2052049.334      160125.252
#Sta/Elev= 30
       0 1905.53    26.2 1899.33    42.6 1896.17    75.3 1888.66   114.6    1881
   167.1 1869.97   203.1 1861.42   219.4 1856.88   235.8 1853.22   265.2 1850.24
   291.4 1845.91   311.1 1845.82   313.5 1845.27   320.9 1843.72   327.4 1844.13
   330.7    1845   343.8 1845.92   392.9 1847.28   419.1 1849.73  428.131851.435
     442 1853.47   461.6 1854.13  481.151856.793   491.1 1859.28   500.9 1862.36
   559.8  1885.7   599.1  1897.4   628.6 1902.87   684.2 1916.77   716.9 1923.77
#Mann= 5 ,-1 , 0
       0     .12       0   313.5    .045       0   330.7     .06       0
  428.13    .016       0  481.15     .06       0
Bank Sta=313.5,330.7
XS Rating Curve= 0 ,0
Exp/Cntr=0.3,0.1

Type RM Length L Ch R = 1 ,3722.3  ,202,202.2,200.6
XS GIS Cut Line= 2
      2052513.31      159489.835     2051981.626      159971.606
#Sta/Elev= 30
       0 1914.93    29.5 1906.79     131 1882.27   199.8 1868.45   262.1 1858.82
  309.851849.306  310.941849.051   330.9 1844.75   350.6 1843.42   366.9 1843.51
   373.6 1842.54     380 1841.78   388.6  1842.7   400.8  1843.6  402.571843.552
   412.8 1843.95   425.9 1846.71   442.3 1847.19   452.1 1851.39  462.731853.788
   482.31858.479  488.781860.287  507.831864.533   524.2  1866.5   537.3 1869.87
     557 1872.04  566.661874.069   602.8 1883.92   661.8 1893.02   717.5 1899.84
#Mann= 12 ,-1 , 0
       0     .12       0  309.85     .06       0  310.94     .12       0
   373.6    .045       0   388.6     .12       0   400.8     .06       0
  402.57    .016       0  462.73     .06       0   482.3     .12       0
  488.78     .06       0  507.83    .016       0  566.66     .06       0
Bank Sta=373.6,388.6
XS Rating Curve= 0 ,0
Exp/Cntr=0.3,0.1

Type RM Length L Ch R = 1 ,3520.1  ,276,270.9,266.8
XS GIS Cut Line= 3
     2052385.594      159329.514     2052023.292      159676.033
     2051932.146      159886.537
#Sta/Elev= 30
       0 1911.38    29.5 1902.64    72.1 1888.16    81.9 1884.38    98.3 1876.32
   114.7 1869.92   180.2 1854.58   203.2  1851.1   239.2 1847.55   294.9    1844
   340.8 1843.97  359.691840.843  362.741840.601   364.9 1840.53   373.5 1839.51
   376.8 1839.56   379.9 1840.72   386.6 1842.86   396.5 1843.17   409.6 1847.51
  421.381848.776   468.6 1851.67   488.2 1855.31   514.4 1862.68   524.3 1864.75
   553.8 1870.08  591.491875.441  624.331879.216   671.7 1884.76   730.7 1890.57
#Mann= 8 ,-1 , 0
       0     .12       0  359.69     .06       0  362.74    .016       0
   364.9    .045       0   379.9    .016       0  421.38     .06       0
  591.49    .016       0  624.33     .06       0
Bank Sta=364.9,379.9
XS Rating Curve= 0 ,0
Exp/Cntr=0.3,0.1

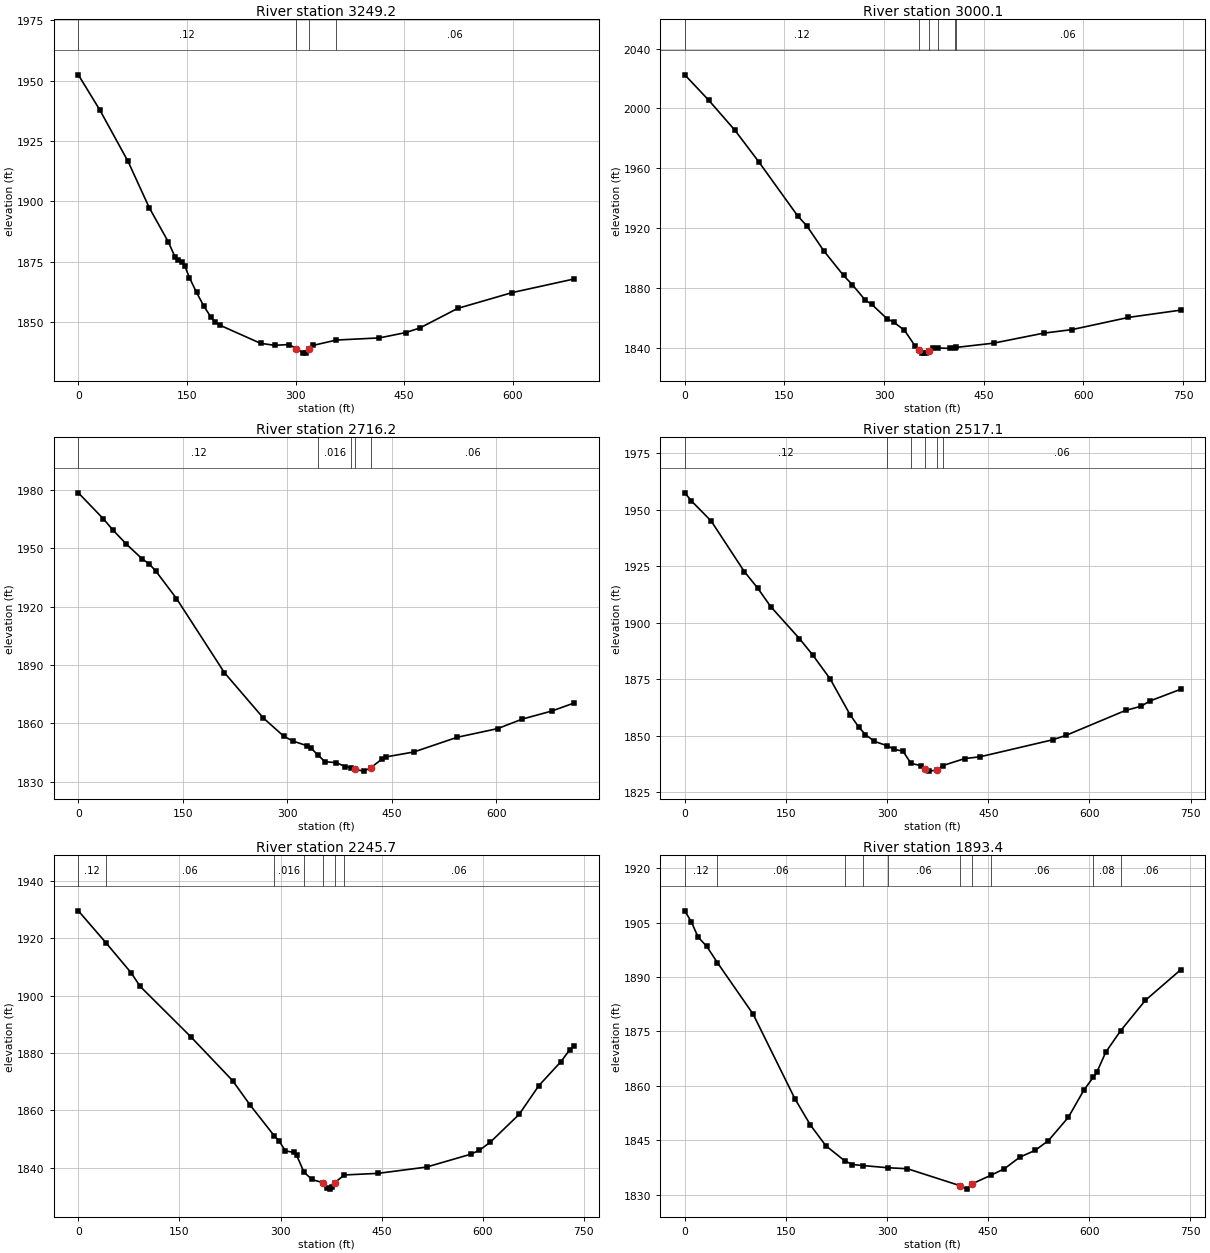
Type RM Length L Ch R = 1 ,3249.2  ,258.7,249.1,237
XS GIS Cut Line= 3
     2052051.504      159087.926     2052018.952      159281.068
     2051732.144      159676.923
#Sta/Elev= 30
       0 1952.47    29.4 1938.03    68.6  1916.6    97.9  1897.4     124 1883.34
   133.8 1876.81   137.1 1875.64   143.6 1874.66   146.9 1873.32   153.4 1868.38
   163.2 1862.27     173 1856.73   182.8 1852.14   189.3 1849.96   195.9 1848.61
   251.6 1841.15   271.3 1840.31     291 1840.65   300.8 1838.96   310.7 1837.08
     314  1837.2   318.8 1838.67   323.8 1840.26   356.31842.507   415.7 1843.39
   451.8 1845.58   471.4 1847.48   523.9 1855.63   599.4  1862.2   684.7 1867.83
#Mann= 4 ,-1 , 0
       0     .12       0   300.8    .045       0   318.8    .016       0
   356.3     .06       0
Bank Sta=300.8,318.8
XS Rating Curve= 0 ,0
Exp/Cntr=0.3,0.1

Type RM Length L Ch R = 1 ,3000.1  ,283.6,284,282.9
XS GIS Cut Line= 2
     2051793.762       158911.85     2051699.942      159652.162
#Sta/Elev= 30
       0  2022.5      36 2005.53    75.3 1985.49   111.3 1964.34   170.2 1927.93
   183.3 1921.68   209.5 1904.58   238.9 1888.28     252 1882.18   271.6 1871.79
   281.5 1868.91   304.4 1859.31   314.2 1857.12   330.6 1851.61   346.9 1840.91
   352.4 1838.15   356.8 1836.63     360 1836.34   363.3 1836.62   367.4 1837.91
   373.1 1839.64  380.841839.735   399.3 1839.54  407.23 1840.09  407.581840.114
   464.8 1843.02     540  1849.7   582.6 1852.06   667.7 1860.23   746.2  1865.1
#Mann= 6 ,-1 , 0
       0     .12       0   352.4    .045       0   367.4     .12       0
  380.84    .016       0  407.23     .12       0  407.58     .06       0
Bank Sta=352.4,367.4
XS Rating Curve= 0 ,0
Exp/Cntr=0.3,0.1

Type RM Length L Ch R = 1 ,2716.2  ,197.1,199.1,200
XS GIS Cut Line= 3
      2051524.16      158903.464     2051474.247      159435.148
     2051448.205      159610.929
#Sta/Elev= 30
       0 1978.45      36 1965.06    49.1 1959.53    68.8 1952.15    91.7 1944.47
   101.6 1941.97   111.4 1938.15   140.9 1924.12   209.7 1885.99   265.4 1862.75
   294.9 1853.32     308 1850.86   327.6 1848.52   334.2 1847.12  344.641843.468
   353.8 1840.26   370.2 1839.74   383.3 1837.72  391.211837.216     397 1836.33
   409.5 1835.39   419.4 1837.03   435.7 1841.55   442.3 1842.75   481.6 1845.23
   543.7 1852.78   601.9 1857.25   637.4 1862.16   679.4 1866.26   711.7 1870.42
#Mann= 5 ,-1 , 0
       0     .12       0  344.64    .016       0  391.21     .06       0
     397    .045       0   419.4     .06       0
Bank Sta=397,419.4
XS Rating Curve= 0 ,0
Exp/Cntr=0.3,0.1

Type RM Length L Ch R = 1 ,2517.1  ,269.9,271.4,269.8
XS GIS Cut Line= 2
     2051368.681      158899.453     2051233.854      159622.144
#Sta/Elev= 30
       0 1957.45     9.8 1953.88    39.2 1944.94    88.2 1922.64   107.8 1915.41
   127.4 1907.11   169.9 1892.99   189.5 1885.78   215.6 1875.11     245 1859.33
   258.1 1853.75   267.9 1850.49     281 1847.52   300.51845.526   310.4 1843.99
   323.5 1843.18  335.231837.811   349.6 1836.78   356.1 1835.21   362.7 1834.34
   374.1 1834.84  382.481836.795     415 1839.89   437.8 1840.68   545.6 1848.21
   565.3 1850.16   653.5 1861.19   676.4 1863.02   689.4 1865.34   735.2 1870.54
#Mann= 6 ,-1 , 0
       0     .12       0   300.5    .016       0  335.23     .12       0
   356.1    .045       0   374.1     .12       0  382.48     .06       0
Bank Sta=356.1,374.1
XS Rating Curve= 0 ,0
Exp/Cntr=0.3,0.1

Type RM Length L Ch R = 1 ,2245.7  ,342.1,352.3,360
XS GIS Cut Line= 2
     2051116.972      158849.149     2050991.019      159573.931
#Sta/Elev= 30
       0 1929.61   40.921918.476    78.5 1907.94    91.6 1903.27   166.8 1885.68
   228.9 1870.35     255 1861.79  290.551851.141   297.5 1849.43   307.3 1845.81
   320.4 1845.32   323.7 1844.43  334.571838.496   346.6 1835.86   362.9 1834.74
   369.5  1832.8   372.7  1832.5     376 1833.09   380.5 1834.78  394.681837.444
   444.7    1838   516.6  1840.2     582 1844.67     595 1846.04   611.4 1848.93
   653.9 1858.57   683.3 1868.63     716 1876.99   729.1 1881.13   735.6 1882.46
#Mann= 7 ,-1 , 0
       0     .12       0   40.92     .06       0  290.55    .016       0
  334.57     .12       0   362.9    .045       0   380.5     .12       0
  394.68     .06       0
Bank Sta=362.9,380.5
XS Rating Curve= 0 ,0
Exp/Cntr=0.3,0.1

Type RM Length L Ch R = 1 ,1893.4  ,395.4,395.9,390.3
XS GIS Cut Line= 2
     2050932.907      158787.627     2050554.425      159418.439
#Sta/Elev= 30
       0 1908.23     9.8 1905.15    19.6 1901.03    32.7  1898.4   48.411893.928
   101.4 1879.73   163.5 1856.35   186.4 1849.16   209.2 1843.46  237.011839.324
   248.5 1838.28  263.891837.996  301.47 1837.38   330.2 1837.12   408.7 1832.42
   418.5 1831.49   425.5 1832.89  454.151835.319   474.1  1837.1     497  1840.3
   519.9 1842.19   539.5 1844.88   568.9 1851.27   591.8 1858.71  606.19  1862.4
   611.4 1863.78   624.5 1869.24  646.651875.185   683.3 1883.55   735.6 1891.96
#Mann= 10 ,-1 , 0
       0     .12       0   48.41     .06       0  237.01     .08       0
  263.89    .016       0  301.47     .06       0   408.7    .045       0
   425.5     .12       0  454.15     .06       0  606.19     .08       0
  646.65     .06       0
Bank Sta=408.7,425.5
XS Rating Curve= 0 ,0
Exp/Cntr=0.3,0.1

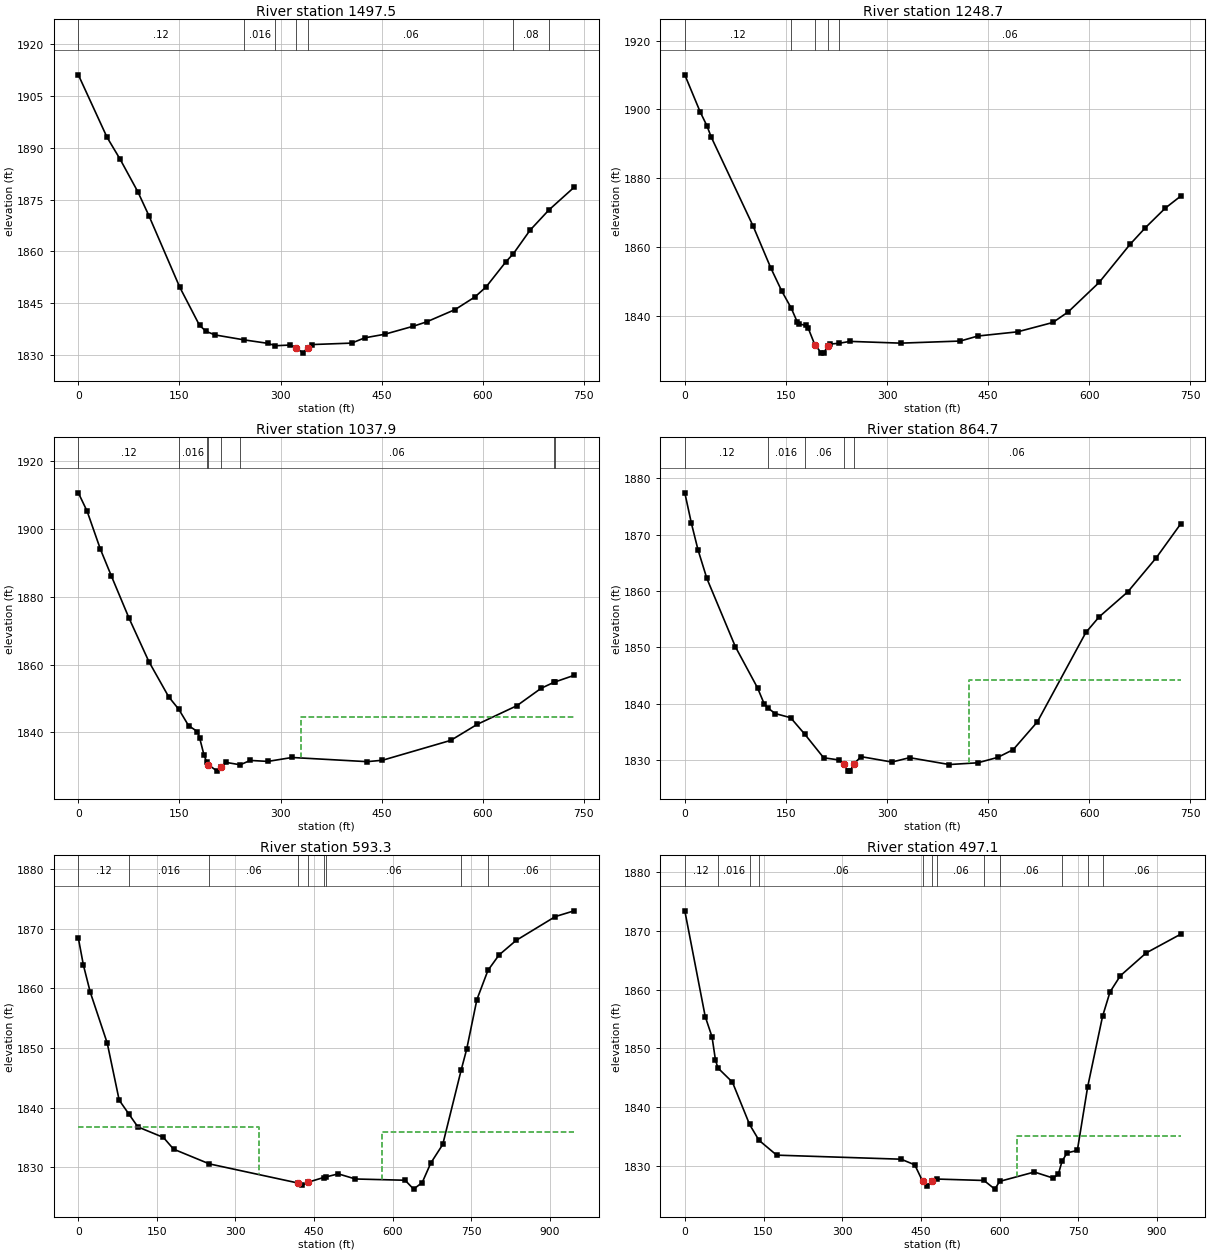
Type RM Length L Ch R = 1 ,1497.5  ,247.4,248.7,250.4
XS GIS Cut Line= 2
      2050672.49      158592.314     2050294.008      159223.126
#Sta/Elev= 30
       0  1911.1    42.5 1893.05    62.1 1886.63    88.3 1877.24   104.6 1870.37
   150.4 1849.65   179.8 1838.58   189.6 1836.84   202.7 1835.81  246.061834.371
   281.2 1833.37  292.381832.677   313.9 1832.88     323 1832.08   333.5 1830.54
     340 1832.15   346.6 1833.02   405.4 1833.44     425 1834.97   454.5    1836
     497 1838.33   516.6 1839.58   559.1 1843.16   588.5 1846.82   604.9 1849.69
   634.3 1856.97  645.561859.358   670.2 1866.13   698.11871.975   735.6 1878.56
#Mann= 7 ,-1 , 0
       0     .12       0  246.06    .016       0  292.38     .06       0
     323    .045       0     340     .06       0  645.56     .08       0
   698.1     .06       0
Bank Sta=323,340
XS Rating Curve= 0 ,0
Exp/Cntr=0.3,0.1

Type RM Length L Ch R = 1 ,1248.7  ,208.4,210.9,211
XS GIS Cut Line= 2
     2050535.772      158498.998     2050157.289       159129.81
#Sta/Elev= 30
       0 1910.05    22.9 1899.24    32.7 1895.29    39.2 1891.97   101.4 1866.08
   127.5 1853.98   143.9  1847.2  157.881842.275   166.8 1838.27     170 1837.66
   179.8 1837.22   183.1 1836.44   192.9 1831.62   202.7 1829.23     206 1829.19
   212.4 1831.39   215.8 1831.83   229.11832.058   245.2  1832.6   320.4 1832.09
   408.7  1832.7   434.8 1834.16   493.7 1835.38     546 1838.09   568.9 1841.18
   614.7 1849.73   660.4 1860.76   683.3 1865.63   712.8 1871.31   735.6 1874.79
#Mann= 5 ,-1 , 0
       0     .12       0  157.88    .016       0   192.9    .045       0
   212.4     .12       0   229.1     .06       0
Bank Sta=192.9,212.4
XS Rating Curve= 0 ,0
Exp/Cntr=0.3,0.1

Type RM Length L Ch R = 1 ,1037.9  ,171.4,173.2,173.6
XS GIS Cut Line= 2
     2050383.862       158368.79     2050005.379      158999.602
#Sta/Elev= 30
       0 1910.73    13.1 1905.26    32.7 1894.09      49 1886.17    75.2 1873.71
   104.6  1860.9     134 1850.49  149.251846.725   163.5 1841.97   176.6 1840.21
   179.8 1838.45   186.4 1833.31  190.521831.155   192.9 1830.39     206 1828.52
   212.4 1829.66   219.1  1831.1   240.21830.391     255 1831.68   281.2 1831.39
   317.1 1832.55   428.3 1831.32   451.2 1831.73   552.6 1837.61   591.8 1842.34
   650.6 1847.84   686.6 1852.99  705.181854.717  707.22 1854.87   735.6 1856.82
#Mann= 8 ,-1 , 0
       0     .12       0  149.25    .016       0  190.52     .12       0
   192.9    .045       0   212.4     .12       0   240.2     .06       0
  705.18     .08       0  707.22     .06       0
#XS Ineff= 2 , 0
                          329.68          1844.4
Permanent Ineff=
       F       F
Bank Sta=192.9,212.4
XS Rating Curve= 0 ,0
Exp/Cntr=0.3,0.1

Type RM Length L Ch R = 1 ,864.7   ,241.6,271.4,295.7
XS GIS Cut Line= 2
     2050236.293      158321.047      2049857.81      158951.859
#Sta/Elev= 30
       0 1877.41     9.8    1872    19.6 1867.29    32.7 1862.22    75.2 1850.05
   107.9 1842.79   117.7 1839.98   123.61839.198     134 1838.23   156.9  1837.5
  177.821834.591     206 1830.38   228.9 1829.99   235.9 1829.26     242 1828.07
   245.2 1828.01   250.9 1829.32   261.6 1830.58   307.3 1829.62   333.5  1830.4
   392.3 1829.18   434.8 1829.49   464.3 1830.45   487.2 1831.82   523.1 1836.76
     595 1852.62   614.7 1855.39   657.2 1859.83   699.7 1865.92   735.6 1871.88
#Mann= 5 ,-1 , 0
       0     .12       0   123.6    .016       0  177.82     .06       0
   235.9    .045       0   250.9     .06       0
#XS Ineff= 2 , 0
                          421.03         1844.14
Permanent Ineff=
       F       F
Bank Sta=235.9,250.9
XS Rating Curve= 0 ,0
Exp/Cntr=0.3,0.1

Type RM Length L Ch R = 1 ,593.3   ,99.8,96.2,97.1
XS GIS Cut Line= 6
     2050202.546      158313.186      2050103.71      158465.899
     2049873.849      158469.371     2049843.294      158487.426
     2049611.349      158498.538     2049525.462      158751.554
#Sta/Elev= 30
       0 1868.45     9.7  1863.9    22.7 1859.39    55.2 1850.83      78 1841.27
   96.09 1838.99   113.7 1836.78   162.4 1835.02   181.9 1833.05  250.121830.583
   418.6 1827.39   427.9 1826.96   437.6 1827.48  468.241828.296  472.721828.391
   496.3 1828.91     529 1828.05   623.9 1827.84   640.2 1826.35   656.6 1827.46
     673 1830.73   695.8 1833.84  730.881846.281   741.4 1849.78     761 1858.13
  782.081863.028   803.3 1865.61   835.9 1868.05   910.8 1872.05   946.7 1873.01
#Mann= 9 ,-1 , 0
       0     .12       0   96.09    .016       0  250.12     .06       0
   418.6    .045       0   437.6     .08       0  468.24    .016       0
  472.72     .06       0  730.88     .08       0  782.08     .06       0
#XS Ineff= 2 , 0
          344.26 1836.71  579.99            1836
Permanent Ineff=
       F       F
Bank Sta=418.6,437.6
XS Rating Curve= 0 ,0
Exp/Cntr=0.3,0.1

Type RM Length L Ch R = 1 ,497.1   ,273.5,248.9,222.6
XS GIS Cut Line= 6
     2050156.973      158254.592     2050041.955      158419.523
     2049791.905       158427.01     2049767.599      158432.565
     2049534.266      158466.593      2049479.89       158692.96
#Sta/Elev= 30
       0  1873.4    38.9 1855.42    51.9 1851.96    58.4 1848.03   63.091846.672
    90.8 1844.25  123.421837.065  141.311834.372   175.1 1831.84   412.2 1831.15
   438.2 1830.19  453.32 1827.37   460.6  1826.6   471.4 1827.39  480.531827.774
  570.081827.531   590.8 1826.06  599.941827.378   666.1 1828.97   702.2 1827.93
     712 1828.66  718.711830.773   728.4 1832.23     748 1832.64  767.621843.441
  796.041855.453   810.3 1859.61     830 1862.36   879.2 1866.24   944.8 1869.42
#Mann= 12 ,-1 , 0
       0     .12       0   63.09    .016       0  123.42     .12       0
  141.31     .06       0  453.32    .045       0   471.4     .08       0
  480.53     .06       0  570.08     .08       0  599.94     .06       0
  718.71    .016       0  767.62     .08       0  796.04     .06       0
#XS Ineff= 2 , 0
                          632.56         1835.07
Permanent Ineff=
       F       F
Bank Sta=453.32,471.4
XS Rating Curve= 0 ,0
Exp/Cntr=0.3,0.1

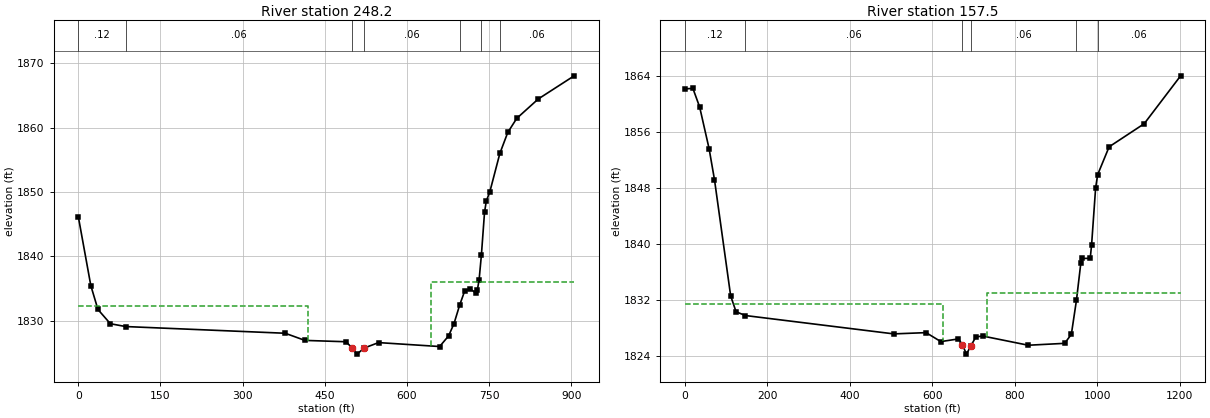
Type RM Length L Ch R = 1 ,248.2   ,89.3,90.6,91.7
XS GIS Cut Line= 4
     2049968.171      158137.405     2049660.011      158159.106
     2049449.508      158495.478     2049456.018       158695.13
#Sta/Elev= 30
       0 1846.15    22.8 1835.47    35.8 1831.76    58.5 1829.55   86.51 1829.11
   377.8 1828.07   413.9 1826.96   489.3 1826.75   500.4 1825.71     509 1824.83
   522.1 1825.78   548.3 1826.62   659.8 1826.01   676.2 1827.66   686.1 1829.58
  696.531832.475   705.7 1834.66   715.6 1834.96   725.4 1834.35   728.7 1834.78
   731.9 1836.36  736.07 1840.19   741.8 1846.82     745 1848.58   751.6 1850.06
   769.81855.986   784.3 1859.25   800.7 1861.43     840 1864.44   905.5 1868.03
#Mann= 7 ,-1 , 0
       0     .12       0   86.51     .06       0   500.4    .045       0
   522.1     .06       0  696.53    .016       0  736.07     .08       0
   769.8     .06       0
#XS Ineff= 2 , 0
          419.45 1832.26   643.3         1836.07
Permanent Ineff=
       F       F
Bank Sta=500.4,522.1
XS Rating Curve= 0 ,0
Exp/Cntr=0.3,0.1

Type RM Length L Ch R = 1 ,157.5   ,160.4,157.5,154.4
XS GIS Cut Line= 4
     2050044.126      158033.238     2049610.098      158094.002
      2049325.81      158504.158     2049401.765      158758.065
#Sta/Elev= 30
       0  1862.1    19.6 1862.18      36 1859.52    58.9 1853.57      72 1849.13
   111.2 1832.54   124.3 1830.27  147.081829.731   506.8 1827.11     585 1827.29
   620.9 1826.01   663.3 1826.39   673.1 1825.59   682.9 1824.22   693.4 1825.37
   705.7 1826.67     722 1826.81   832.9 1825.49     921 1825.76   937.3 1827.04
  949.741831.932   960.2 1837.18   963.5 1837.89   983.1  1837.9   986.4 1839.82
   996.2 1847.98 1001.111849.848  1028.9 1853.83    1114 1857.13  1202.3 1863.97
#Mann= 6 ,-1 , 0
       0     .12       0  147.08     .06       0   673.1    .045       0
   693.4     .06       0  949.74    .016       0 1001.11     .06       0
#XS Ineff= 2 , 0
          625.21 1831.43  732.05         1832.98
Permanent Ineff=
       F       F
Bank Sta=673.1,693.4
XS Rating Curve= 0 ,0
Exp/Cntr=0.3,0.1

Chan Stop Cuts=-1
Use User Specified Reach Order=0
Composite Channel Slope=5